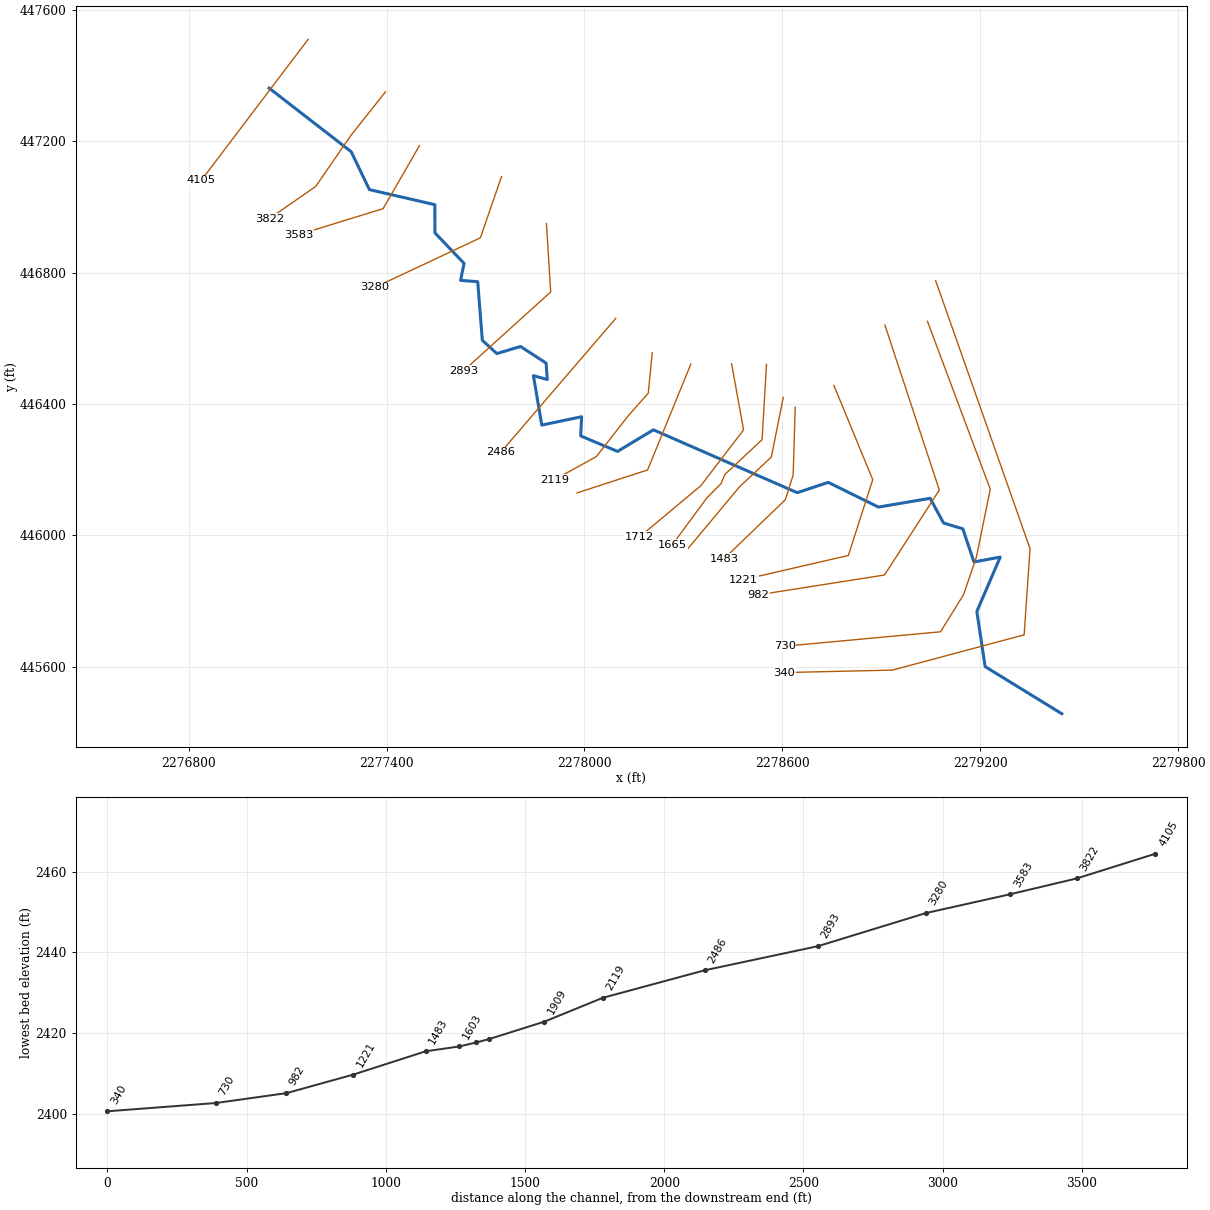
--- GUYRN.prj (project) ---

Proj Title=GUYRN
Current Plan=p01
Default Exp/Contr=0,0
English Units
Geom File=g01
Flow File=f01
Plan File=p01
Background Map Layer=Inundation Boundary (01pct Value_0)
BEGIN DESCRIPTION:
 ----------MODEL BY WOOD PLC 2021----------
Stream Name:  Guy Run
Flood Zone: Enhanced Approximate
Pocahontas County, WV
HEC-RAS Version: RAS 6.1
Vertical Datum: NAVD88
Projection: NAD 1983 StatePlane West Virginia S FIPS 4702 (US Feet)
Terrain: 1-meter LIDAR (FEMA Region III 3DEP collected 2016-2018)
Land Use: 2019 NLCD
Hydrologic Method:
WV SIR2010-5033 regression equations
Model Notes:
Normal depth tie in to Knapp Creek
END DESCRIPTION:
DSS Export Rating Curves= 0
DSS Export Rating Curve Sorted= 0
DSS Export Volume Flow Curves= 0
DXF OffsetX= 0
DXF OffsetY= 0
DXF ScaleX= 0
DXF ScaleY= 0

--- GUYRN.p01 (plan) ---

Plan Title=Floodplain
Program Version=6.10
Short Identifier=Floodplain
Geom File=g01
Flow File=f01
Subcritical Flow
K Sum by GR= 0
Std Step Tol= 0.01
Critical Tol= 0.01
Num of Std Step Trials= 20
Max Error Tol= 0.3
Flow Tol Ratio= 0.001
Split Flow NTrial= 30
Split Flow Tol= 0.02
Split Flow Ratio= 0.02
Log Output Level= 0
Friction Slope Method= 1
Unsteady Friction Slope Method= 2
Unsteady Bridges Friction Slope Method= 1
Parabolic Critical Depth
Global Vel Dist= 0 , 0 , 0
Global Log Level= 0
CheckData=True
Encroach Param=-1 ,0,0, 0
Mapping Interval=1HOUR
Computation Time Step Use Courant=        0
Computation Time Step Use Time Series=    0
Computation Time Step Count To Double=0
Computation Time Step Max Doubling=0
Computation Time Step Max Halving=0
Computation Time Step Residence Courant=0
Run HTab= 0
Run UNet= 0
Run Sediment= 0
Run PostProcess= 0
Run WQNet= 0
Run RASMapper=-1
UNET Theta= 0
UNET Theta Warmup= 0
UNET ZTol= 0
UNET ZSATol= 0
UNET MxIter= 0
UNET Max Iter WO Improvement= 0
UNET MaxInSteps= 0
UNET DtIC= 0
UNET DtMin= 0
UNET MaxCRTS= 0
UNET WFStab= 0
UNET SFStab= 0
UNET WFX= 1
UNET SFX= 1
UNET Gravity=32.174
UNET 1D Methodology=Finite Difference
UNET DSS MLevel= 1
UNET Pardiso=0
UNET DZMax Abort= 0
UNET Use Existing IB Tables= 0
UNET Froude Reduction=False
UNET Froude Limit= 0
UNET Froude Power= 0
UNET D1 Cores= 0
UNET WindReference=Eulerian
UNET WindDragFormulation=Hsu (1988)
UNET D2 Coriolis=0
UNET D2 Cores= 0
UNET D2 Theta= 1
UNET D2 Theta Warmup= 1
UNET D2 Z Tol= 0.01
UNET D2 Volume Tol= 0.01
UNET D2 Max Iterations= 20
UNET D2 Equation= 0
UNET D2 RampUpFraction=0.1
UNET D2 TimeSlices= 1
UNET D2 Turbulence Formulation=Non-Conservative (original)
UNET D2 Eddy Viscosity=0.3
UNET D2 Transverse Eddy Viscosity=0.1
UNET D2 Smagorinsky Mixing=0
UNET D2 BCVolumeCheck=0
UNET D2 Cores=0
UNET D2 SolverType=PARDISO (Direct)
UNET D2 Minimum Iterations= 2147483647
UNET D2 Maximum Iterations= 2147483647
UNET D2 Restart Number= 10
UNET D2 Relaxation Coeff=1.3
UNET D2 SOR Precondition Iterations= 10
UNET D2 ILUT Maximum Fill= 8
UNET D2 ILUT Tolerance=1E-08
UNET D1D2 MaxIter= 0
UNET D1D2 ZTol=0.01
UNET D1D2 QTol=0.1
UNET D1D2 MinQTol=1
Write IC File= 0
Write IC File at Fixed DateTime=0
Write IC File at Sim End=0
Echo Input=False
Echo Parameters=False
Echo Output=False
Write Detailed= 0
HDF Write Warmup=0
HDF Write Time Slices=0
HDF Flush=0
HDF Compression= 1
HDF Chunk Size= 1
HDF Spatial Parts= 1
HDF Use Max Rows=0
HDF Fixed Rows= 1
Calibration Method= 0
Calibration Iterations= 20
Calibration Max Change=0.05
Calibration Tolerance=0.2
Calibration Maximum=1.5
Calibration Minimum=0.5
Calibration Optimization Method= 1
WQ AD Non Conservative
WQ ULTIMATE=-1
WQ Max Comp Step=1HOUR
WQ Output Interval=15MIN
WQ Output Selected Increments= 0
WQ Output face flow=0
WQ Output face velocity=0
WQ Output face area=0
WQ Output face dispersion=0
WQ Output cell volume=0
WQ Output cell surface area=0
WQ Output cell continuity=0
WQ Output cumulative cell continuity=0
WQ Output face conc=0
WQ Output face dconc_dx=0
WQ Output face courant=0
WQ Output face peclet=0
WQ Output face adv mass=0
WQ Output face disp mass=0
WQ Output cell mass=0
WQ Output cell source sink temp=0
WQ Output nsm pathways=0
WQ Output nsm derived pathways=0
WQ Create Restart=0
WQ Fixed Restart=0
WQ System Summary=0
WQ Write To DSS=0
Sorting and Armoring Iterations= 10
XS Update Threshold= 0.02
Bed Roughness Predictor= 0
Hydraulics Update Threshold= 0.02
Energy Slope Method= 1
Volume Change Method= 1
Sediment Retention Method= 0
Sediment TS Multiplier= 1
Warm Up Method= 0
XS Weighting Method= 0
Number of US Weighted Cross Sections= 1
Number of DS Weighted Cross Sections= 1
Upstream XS Weight=0
Main XS Weight=1
Downstream XS Weight=0
Number of DS XS's Weighted with US Boundary= 1
Upstream Boundary Weight= 1
Weight of XSs Associated with US Boundary= 0
Number of US XS's Weighted with DS Boundary= 1
Downstream Boundary Weight= 0.5
Weight of XSs Associated with DS Boundary= 0.5
Percentile Method= 0
Sediment Output Level= 3
Mass or Volume Output= 0
Output Increment Type= 1
Profile and TS Output Increment= 1
Transport Output Increment 1
XS Output Flag= 0
XS Output Increment= 10
Read HDF5 Sediment Hotstart= 0
Sediment Hotstart Type= 0
Write Gradation File= 0
Read Gradation Hotstart= 0
Write HDF5 File= 1
Write Binary Output= 1
Write DSS Sediment File= 0
DSS Sediment Output Type= 1
SV Curve= 0
Specific Gage Flag= 0
Subcell Erosion Methods= 0
Subcell Deposition Methods= 0
Advection Scheme= 1
Matrix Solver= 0
Implicit Weighting Factor= 1
Maximum Outer Loop Convergence Iterations= 5
Convergence Maximum Absolute= 0.001
Convergence RMSE= 0.0001
Grain Fractions Max Abs Error= 0.001
Max Subgrid Regions= 1
Max Subgrid Length Scale= 3.402823E+38
Initial Layer Thickness= 3.402823E+38
Min Layer Thickness= 3.402823E+38
Max Layer Thickness= 3.402823E+38
Number of Layers= 5

--- GUYRN.f01 (steady flow) ---

Flow Title=Flow
Program Version=6.10
Number of Profiles= 6
Profile Names=01pct,10pct,04pct,02pct,0_2pct,01plus
River Rch & RM=GUYRN,Main            ,4105
     558     295     392     472     780     825
Boundary for River Rch & Prof#=GUYRN,Main            , 1
Up Type= 0
Dn Type= 3
Dn Slope=0.00558
Boundary for River Rch & Prof#=GUYRN,Main            , 2
Up Type= 0
Dn Type= 3
Dn Slope=0.00558
Boundary for River Rch & Prof#=GUYRN,Main            , 3
Up Type= 0
Dn Type= 3
Dn Slope=0.00558
Boundary for River Rch & Prof#=GUYRN,Main            , 4
Up Type= 0
Dn Type= 3
Dn Slope=0.00558
Boundary for River Rch & Prof#=GUYRN,Main            , 5
Up Type= 0
Dn Type= 3
Dn Slope=0.00558
Boundary for River Rch & Prof#=GUYRN,Main            , 6
Up Type= 0
Dn Type= 3
Dn Slope=0.00558
DSS Import GetInterval= 0
DSS Import GetPeak= 0
DSS Import FillOption= 0

--- GUYRN.g01 (geometry) ---

Geom Title=Geometry
Program Version=6.10

River Reach=GUYRN           ,Main
Reach XY= 30
     2277043.787      447361.138     2277292.723      447167.552
     2277347.898      447052.261     2277546.453      447006.413
     2277546.551      446920.827     2277634.947       446827.82
      2277624.36      446776.185     2277676.335      446772.131
     2277690.374      446593.646     2277734.482      446553.366
     2277806.073         446575.     2277883.745      446524.474
     2277887.259      446474.609     2277845.281      446486.016
     2277870.659        446335.8     2277991.501      446361.281
     2277988.658       446302.85     2278100.348      446255.751
     2278209.138      446321.421     2278645.343      446130.215
     2278739.241       446161.57     2278891.565      446086.399
     2279048.399      446113.053     2279089.024      446037.883
     2279147.589       446020.17     2279181.138      445919.423
      2279260.86      445934.169     2279189.991      445768.737
     2279215.141      445601.016     2279447.627      445457.629

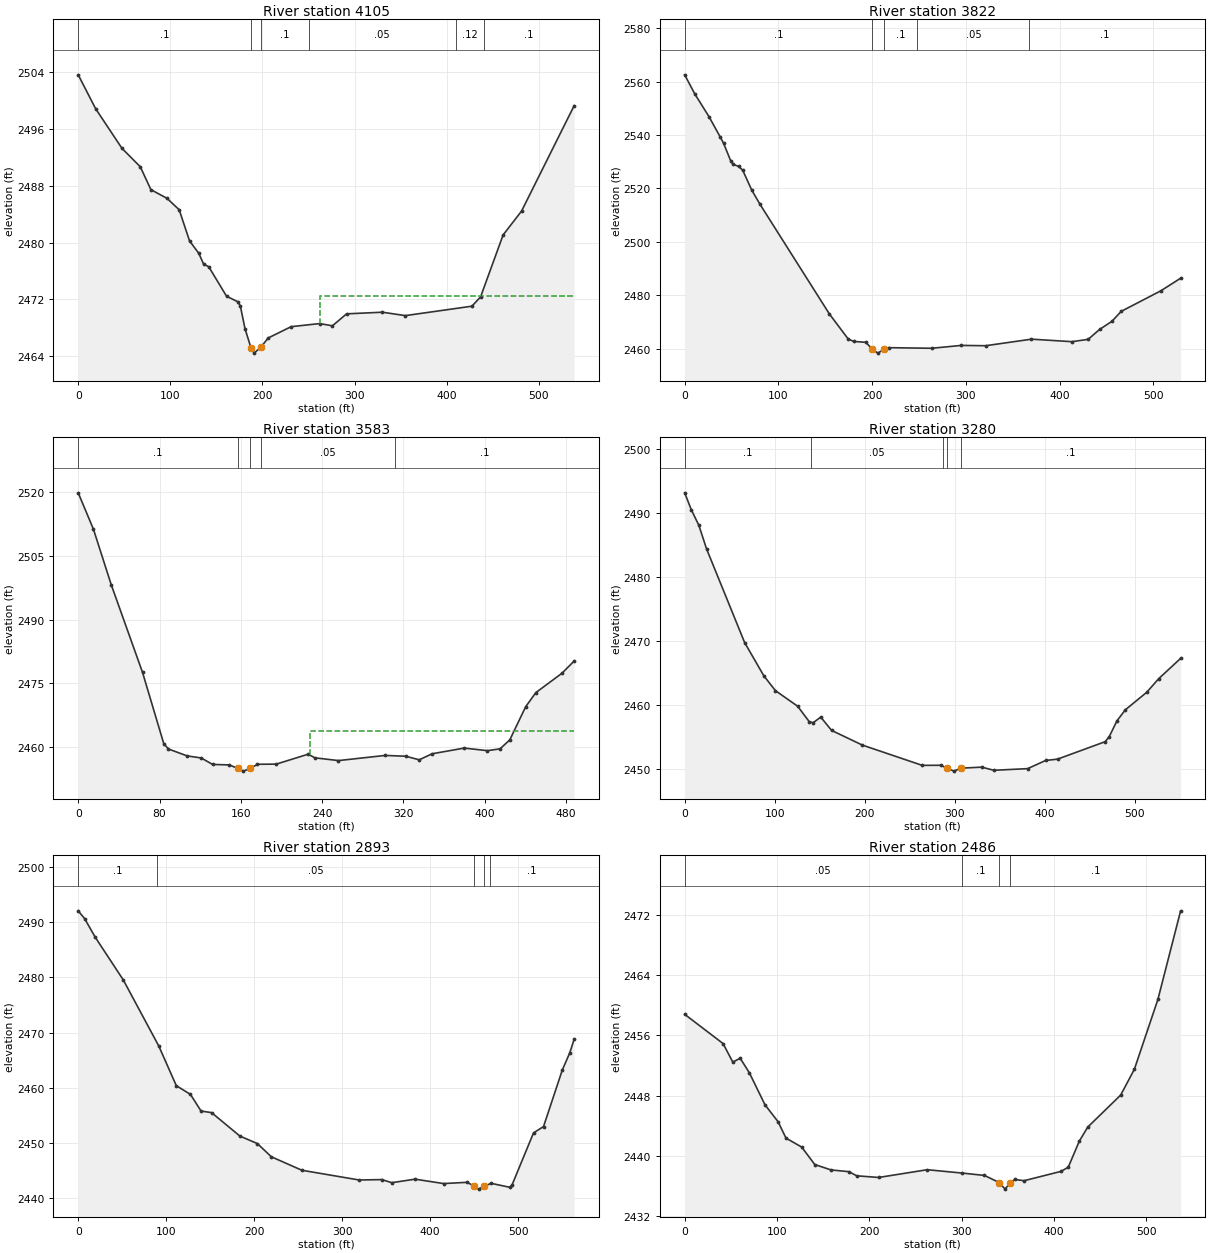
Type RM Length L Ch R = 1 ,4105    ,282.3,282.3,282.3
XS GIS Cut Line= 2
2277162.22856833447509.5972932942276837.73065524 447080.11476126
#Sta/Elev= 30
       0 2503.66    18.9 2498.88    47.5 2493.29    67.4 2490.69    78.9 2487.46
    96.3 2486.25   109.6 2484.63   120.8 2480.25   130.9 2478.48   136.1 2476.97
   141.7 2476.59     161 2472.44   173.1 2471.66     176 2471.05     181 2467.88
   187.4  2465.2     191 2464.41   198.8 2465.32   206.1 2466.54   231.1 2468.14
   262.2 2468.58   275.9 2468.26   291.3 2469.95   330.2 2470.18   355.1  2469.7
   427.3 2471.03   436.7 2472.33   461.2 2481.08   481.2 2484.44   538.3 2499.31
#Mann= 6 ,-1,0
       0      .1       0   187.4    .045       0   198.8      .1       0
     250     .05       0     410     .12       0     440      .1       0
#XS Ineff= 2 , 0
           159.3 2460.94  262.13         2472.44
Permanent Ineff=
       F       F
Bank Sta=187.4,198.8
XS Rating Curve= 0 ,0
Exp/Cntr(USF)=0,0
Exp/Cntr=0.3,0.1

Type RM Length L Ch R = 1 ,3822    ,239,239,239
XS GIS Cut Line= 4
2277396.61885471447349.6839930642277292.11729655447217.652822031
2277184.74666354447061.6075020592277044.07071847446963.824838134
#Sta/Elev= 30
       0 2562.52    10.8 2555.37    26.2  2546.7    37.7 2539.38    41.5 2536.88
    49.1 2530.32    51.9 2528.95    57.6 2528.23    61.9  2526.8    71.6 2519.32
    80.4 2514.01   154.4 2472.96   174.4 2463.62   180.2 2462.69   193.2 2462.34
   200.3 2459.76   206.1  2458.3   212.7 2459.78   217.5 2460.34   263.6 2460.12
   295.2 2461.19   321.1 2461.07     370 2463.53   413.1 2462.59   430.4 2463.45
   442.6 2467.15   455.9 2470.24   465.7 2473.94     508 2481.64   529.1 2486.35
#Mann= 5 ,-1,0
       0      .1       0   200.3    .045       0   212.7      .1       0
  248.38     .05       0   367.8      .1       0
Bank Sta=200.3,212.7
XS Rating Curve= 0 ,0
Exp/Cntr=0.3,0.1

Type RM Length L Ch R = 1 ,3583    ,303.4,303.4,303.4
XS GIS Cut Line= 3
2277499.70052037447186.1574363492277389.46667048446994.321905373
2277134.64036814446915.583441167
#Sta/Elev= 30
       0 2519.82      15 2511.25    32.6 2498.14    63.3 2477.59    84.2 2460.84
    88.8 2459.59   107.2 2457.97   121.1 2457.48   132.2 2455.96   148.8 2455.85
   156.82455.039   162.6 2454.39  169.41 2455.04   176.4    2456   194.9 2456.04
   226.4 2458.38   232.8 2457.52   256.1 2456.87   302.1 2458.08   322.3 2457.89
   335.6 2457.05   348.2 2458.47   379.9 2459.81   402.6  2459.2   415.1 2459.63
   424.7 2461.75   440.3 2469.53   450.3 2472.85   475.9 2477.38     488 2480.28
#Mann= 5 ,-1,0
       0      .1       0   156.8    .045       0  169.41      .1       0
     180     .05       0  311.25      .1       0
#XS Ineff= 2 , 0
                          227.61         2463.91
Permanent Ineff=
       F       F
Bank Sta=156.8,169.41
XS Rating Curve= 0 ,0
Exp/Cntr(USF)=0,0
Exp/Cntr=0.3,0.1

Type RM Length L Ch R = 1 ,3280    ,387.3,387.3,387.3
XS GIS Cut Line= 3
 2277748.6728654447092.1611020332277684.37800914446905.562182086
2277364.45410415446754.829181616
#Sta/Elev= 30
       0 2493.11     7.4 2490.46    15.8 2488.03    24.3 2484.37    66.6 2469.77
    87.9 2464.59   100.8 2462.27   125.5 2459.84   138.5 2457.41   142.8 2457.28
   151.2 2458.14   163.2 2456.07   197.4 2453.78   263.9 2450.62     285 2450.63
  291.61 2450.13   299.3 2449.72306.6065 2450.18   330.1 2450.34   343.5 2449.85
   381.1 2450.11     401 2451.38   414.3 2451.59   467.3 2454.32   471.7  2455.1
   480.3 2457.57   489.6 2459.28   513.4 2462.02   526.7 2464.14     551  2467.3
#Mann= 5 ,-1,0
       0      .1       0     140     .05       0  287.37      .1       0
  291.61    .045       0306.6065      .1       0
Bank Sta=291.61,306.6065
XS Rating Curve= 0 ,0
Exp/Cntr=0.3,0.1

Type RM Length L Ch R = 1 ,2893    ,407,407,407
XS GIS Cut Line= 3
2277884.80319076 446948.510435292277897.68766672446740.927211473
2277634.27171374446501.848601974
#Sta/Elev= 30
       0 2492.11     7.3 2490.69    19.4  2487.3    51.2 2479.56    91.5 2467.57
   111.5 2460.34   127.6 2458.75   139.6 2455.73   151.6 2455.44   183.7 2451.19
   203.7 2449.81   219.5 2447.42   254.2 2444.97   319.3  2443.2   345.1 2443.27
   356.4 2442.71   382.9 2443.35   415.3 2442.55   442.3 2442.78     450 2442.06
   455.2 2441.54   460.9 2442.07   469.5 2442.59   490.9 2441.86   493.3 2442.38
   517.5 2451.75   528.9 2452.91   550.3 2463.21   558.8 2466.34   563.7 2468.78
#Mann= 5 ,-1,0
       0      .1       0      90     .05       0     450    .045       0
   460.9     .05       0  467.98      .1       0
Bank Sta=450,460.9
XS Rating Curve= 0 ,0
Exp/Cntr(USF)=0,0
Exp/Cntr=0.3,0.1

Type RM Length L Ch R = 1 ,2486    ,366.7,366.7,366.7
XS GIS Cut Line= 2
2278095.24963146446660.7571388272277745.93717207446252.748733395
#Sta/Elev= 30
       0  2458.8    41.6 2454.91    52.1 2452.45    60.1 2452.96      70 2451.04
      87 2446.77   101.2 2444.52   109.7 2442.35   126.7 2441.16   140.9 2438.84
   158.5 2438.12   177.8 2437.89   186.3 2437.34   210.1 2437.12   262.7 2438.15
     300 2437.71   324.6 2437.39   340.82436.435     347 2435.57   352.2 2436.38
   357.5 2436.85   367.6 2436.69   407.6 2437.93   415.4 2438.48   427.4 2441.95
   436.5 2443.81   472.2 2448.07     487 2451.49   512.5 2460.78   537.1 2472.55
#Mann= 4 ,-1,0
       0     .05       0     300      .1       0   340.8    .045       0
   352.2      .1       0
Bank Sta=340.8,352.2
XS Rating Curve= 0 ,0
Exp/Cntr(USF)=0,0
Exp/Cntr=0.3,0.1

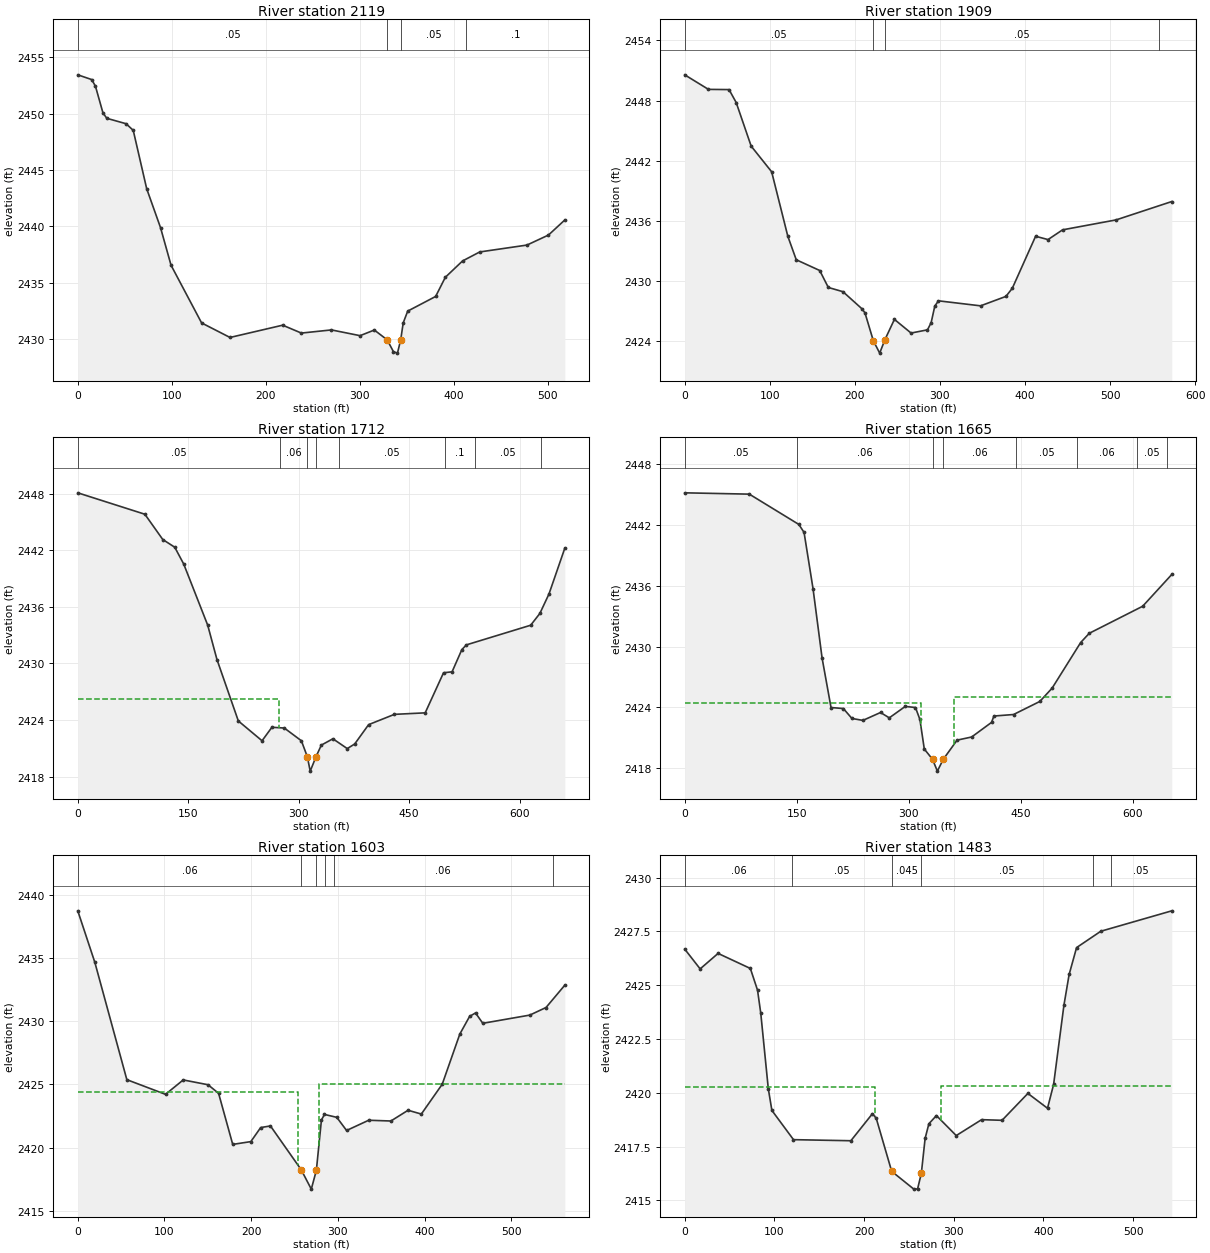
Type RM Length L Ch R = 1 ,2119    ,210.3,210.3,210.3
XS GIS Cut Line= 5
2278205.58255203 446555.882807982278193.56648756446432.915460884
2278133.38927092446364.803074618 2278036.0335488446239.950359692
2277908.96759977446169.651735891
#Sta/Elev= 30
       0 2453.45    14.8 2453.03    18.8 2452.44    26.8 2450.07    30.9 2449.59
    51.4 2449.11      59 2448.52    73.3 2443.34      88 2439.89    99.2 2436.55
   131.7 2431.43   161.9 2430.14   217.9 2431.23   237.8 2430.53   269.8 2430.81
   300.2  2430.3   315.4  2430.8329.08622429.927   335.7 2428.88     340 2428.75
343.48622429.952   346.1 2431.43   350.9 2432.48   380.6 2433.78   390.9 2435.48
   409.2 2436.93   427.5 2437.73   477.7 2438.34   500.6 2439.23     518 2440.57
#Mann= 4 ,-1,0
       0     .05       0329.0862    .045       0343.4862     .05       0
  412.76      .1       0
Bank Sta=329.0862,343.4862
XS Rating Curve= 0 ,0
Exp/Cntr(USF)=0,0
Exp/Cntr=0.3,0.1

Type RM Length L Ch R = 1 ,1909    ,196.7,196.7,196.7
XS GIS Cut Line= 3
2278322.70669284446521.4808114482278191.56824731446199.306790325
2277977.85773937446129.630407545
#Sta/Elev= 30
       0 2450.56    27.9 2449.11    52.1 2449.09    60.5  2447.8    78.1 2443.46
   102.2  2440.9   121.2 2434.48   131.1 2432.14   158.7 2431.07   168.8 2429.38
     186 2428.96   208.3 2427.26   211.9 2426.85   221.7 2424.08   229.2 2422.84
   235.4 2424.19   246.5  2426.2   266.1 2424.84   285.4 2425.16   289.7 2425.88
     294 2427.53   298.3 2428.05   347.8 2427.55   377.6 2428.49   385.1  2429.3
   412.5 2434.48   427.1 2434.15   444.2 2435.12   507.1 2436.11   572.6 2437.94
#Mann= 4 ,-1,0
       0     .05       0   221.7    .045       0   235.4     .05       0
  557.84      .1       0
Bank Sta=221.7,235.4
XS Rating Curve= 0 ,0
Exp/Cntr=0.3,0.1

Type RM Length L Ch R = 1 ,1712    ,47.1,47.1,47.1
BEGIN DESCRIPTION:
structure xs 4
END DESCRIPTION:
XS GIS Cut Line= 4
2278446.20029493446522.7859974872278482.59027114446321.240354642
2278352.71846967  446151.19144282278166.85054001445995.352815981
#Sta/Elev= 30
       0 2448.08    91.1 2445.81   115.4 2443.13   131.7 2442.31   143.9 2440.52
   176.4 2434.05     189  2430.4     218 2423.89   250.2 2421.79   263.6 2423.22
   280.4 2423.14   303.6 2421.79  311.62 2420.11   315.6 2418.57   323.6 2420.12
   330.7 2421.33   346.4    2422   365.9 2420.96     376 2421.45   394.9  2423.5
   429.9 2424.59   471.7 2424.75   496.6    2429   508.2  2429.1   521.5 2431.46
   527.7 2431.96   614.9 2434.04   627.4 2435.29   639.8 2437.36   661.3 2442.22
#Mann= 8 ,-1,0
       0     .05       0   274.8     .06       0  311.62    .045       0
   323.6     .06       0   354.8     .05       0  498.77      .1       0
  538.77     .05       0  628.77      .1       0
#XS Ineff= 2 , 0
          273.69  2426.2
Permanent Ineff=
       F       F
Bank Sta=311.62,323.6
XS Rating Curve= 0 ,0
Exp/Cntr(USF)=0,0
Exp/Cntr=0.5,0.3

Type RM Length L Ch R = 1 ,1665    ,61.3,61.3,61.3
BEGIN DESCRIPTION:
structure xs 3; 14.2 ft between structure and xs
END DESCRIPTION:
XS GIS Cut Line= 6
2278552.05405745446520.7235282432278538.69390675446291.401712406
2278425.94130872446185.8078346332278414.60544385446158.225898281
2278371.46720948446114.4714034182278266.66576242445972.086399406
#Sta/Elev= 30
       0 2445.19    86.5 2445.06   152.8 2442.07   159.8 2441.28   171.8 2435.73
   183.9 2428.89   195.9 2423.99   212.4 2423.89   223.9 2422.91   238.6 2422.72
   262.2  2423.5   273.9 2422.97   295.3  2424.1     309 2423.99   314.9 2422.81
   320.8 2419.89331.77722418.882   338.3 2417.71346.27722418.887   364.7 2420.77
   384.2 2421.08   410.8 2422.52     414 2423.15   440.3  2423.3   475.5 2424.59
     492 2425.91   530.2 2430.41   541.7 2431.32   613.2 2433.99   652.2 2437.13
#Mann= 8 ,-1,0
       0     .05       0     150     .06       0331.7772    .045       0
346.2772     .06       0  444.01     .05       0  525.45     .06       0
  605.45     .05       0  645.45     .06       0
#XS Ineff= 2 , 0
           316.5  2424.4     360            2425
Permanent Ineff=
       F       F
Bank Sta=331.7772,346.2772
XS Rating Curve= 0 ,0
Exp/Cntr=0.5,0.3

Type RM Length L Ch R = 1 ,1603    ,120.7,120.7,120.7
BEGIN DESCRIPTION:
structure xs 2; 8.7 ft between structure and xs
END DESCRIPTION:
XS GIS Cut Line= 4
  2278602.950585 446420.466162852278566.79551569446238.647133683
2278470.44901085446148.1474712932278314.33832347445960.490371042
#Sta/Elev= 30
       0 2438.74    19.7 2434.66    56.6 2425.38   101.2 2424.22   121.6 2425.36
   150.2 2424.98   162.4  2424.3   178.7 2420.26   199.6 2420.48   210.9 2421.59
   222.2 2421.72257.63922418.257   269.3 2416.72275.1392  2418.2     281 2422.19
   284.5 2422.63   298.7  2422.4     310 2421.36   335.5 2422.17   361.1 2422.11
   380.9 2422.96   396.2 2422.66   420.3 2425.02   440.6 2428.99   451.9 2430.39
   458.7 2430.66   467.1 2429.84   521.3 2430.49     540 2431.09   561.7 2432.86
#Mann= 6 ,-1,0
       0     .06       0257.6392    .045       0275.1392     .06       0
  285.38     .05       0  295.38     .06       0  547.56     .05       0
#XS Ineff= 2 , 0
             254  2424.4     278            2425
Permanent Ineff=
       F       F
Bank Sta=257.6392,275.1392
XS Rating Curve= 0 ,0
Exp/Cntr(USF)=0,0
Exp/Cntr=0.5,0.3

Type RM Length L Ch R = 1 ,1483    ,261.3,261.3,261.3
BEGIN DESCRIPTION:
structure xs 1
END DESCRIPTION:
XS GIS Cut Line= 4
  2278639.238377446390.3765328622278632.92498378446183.838383206
2278609.47523753446109.1084226332278423.85636914445929.567628735
#Sta/Elev= 30
       0 2426.68    17.2 2425.76    37.2 2426.48    73.2 2425.78    81.2 2424.77
    84.8  2423.7    93.2 2420.19    97.2 2419.18   121.3 2417.82   185.3 2417.77
   209.4 2419.03   213.6 2418.81230.80062416.348   255.5 2415.52   259.7 2415.53
   263.9 2416.26   268.1 2417.88   272.3 2418.56   280.7 2418.94   302.8 2418.01
   331.1 2418.75   353.9 2418.72   382.7 2419.97   404.6 2419.28   411.4 2420.39
   422.9 2424.07   428.7  2425.5     437 2426.75     464 2427.51   543.2 2428.46
#Mann= 6 ,-1,0
       0     .06       0     120     .05       0230.8006    .045       0
   263.9     .05       0  454.96     .06       0  474.96     .05       0
#XS Ineff= 2 , 0
          211.94 2420.27  286.31         2420.31
Permanent Ineff=
       F       F
Bank Sta=230.8006,263.9
XS Rating Curve= 0 ,0
Exp/Cntr(USF)=0,0
Exp/Cntr=0.3,0.1

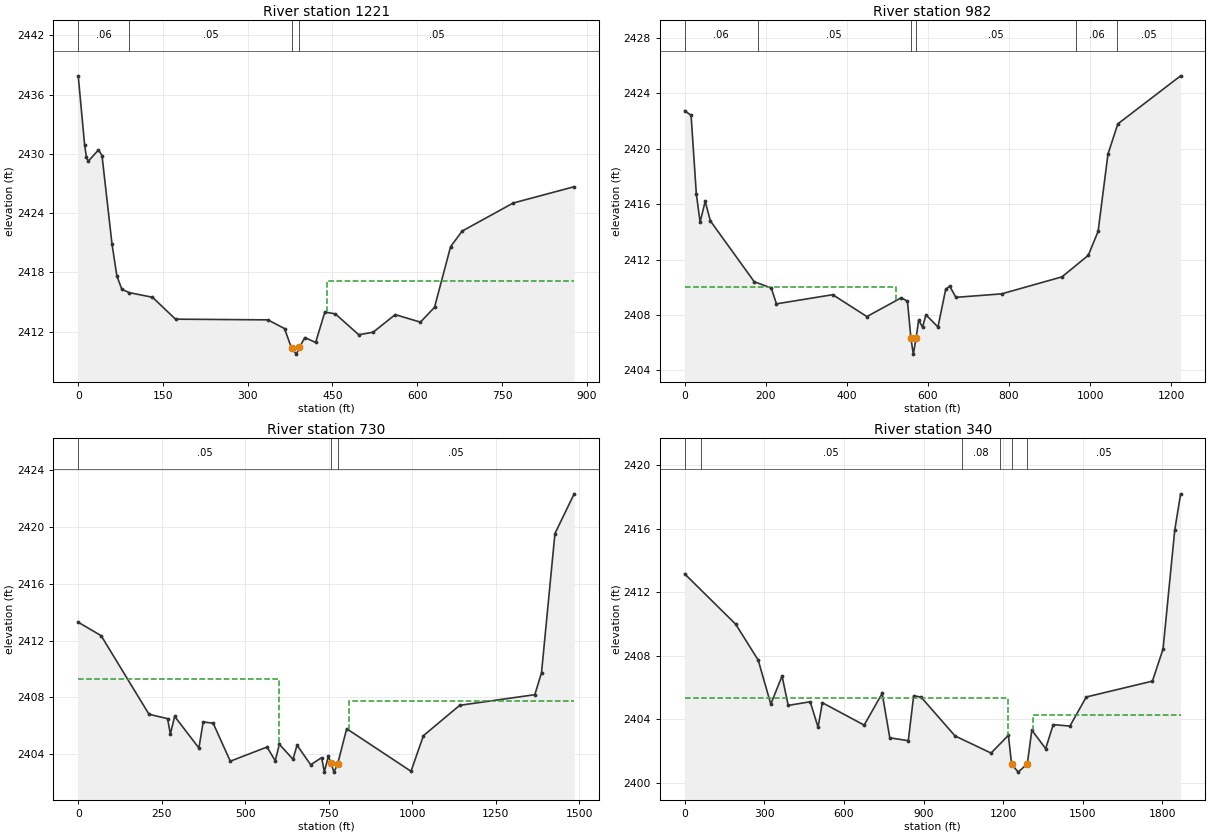
Type RM Length L Ch R = 1 ,1221    ,239,239,239
XS GIS Cut Line= 4
2278756.55679038446456.4680985652278874.23501347446169.782552404
2278800.39241575445939.2209508142278483.04634279445865.709405761
#Sta/Elev= 30
       0 2437.91    11.4 2430.88    14.5 2429.71    17.6 2429.25    35.9 2430.41
    42.1 2429.84    59.8 2420.88    68.4 2417.65    77.1 2416.31      90 2415.96
   131.4 2415.49   172.2 2413.27   335.7  2413.2   365.1 2412.32   377.7 2410.31
   386.1 2409.73   391.5 2410.42   401.1 2411.41   420.2 2410.91   436.5    2414
   455.2  2413.8   496.5 2411.69     522 2411.95     561 2413.73   605.6 2412.97
   630.6 2414.47     659 2420.61   679.5 2422.19   769.8 2425.03   877.7 2426.68
#Mann= 4 ,-1,0
       0     .06       0      90     .05       0   377.7    .045       0
   391.5     .05       0
#XS Ineff= 2 , 0
                          440.56         2417.15
Permanent Ineff=
       F       F
Bank Sta=377.7,391.5
XS Rating Curve= 0 ,0
Exp/Cntr=0.3,0.1

Type RM Length L Ch R = 1 ,982     ,252.8,252.8,252.8
XS GIS Cut Line= 4
2278911.19890902446640.1364430942279076.21999048446138.215715169
 2278909.8958886445879.6660809042278527.24152538445819.395324377
#Sta/Elev= 30
       0 2422.74    15.8 2422.41    28.7 2416.75      38  2414.7    50.6  2416.2
    63.3 2414.79   171.5  2410.4   213.6 2409.94   226.3  2408.8   365.2 2409.46
   449.4 2407.88   534.3 2409.24   549.4 2408.99   558.1  2406.3   563.9 2405.17
  570.77 2406.32   577.1 2407.63   586.7 2407.12     595 2408.01   624.7 2407.13
   643.7 2409.84   653.6 2410.08   668.9 2409.27   781.7 2409.52   930.7 2410.75
   995.4  2412.3  1019.7 2414.03    1044 2419.61  1068.3 2421.79  1223.2 2425.26
#Mann= 6 ,-1,0
       0     .06       0     180     .05       0   558.1    .045       0
  570.77     .05       0  965.78     .06       0 1065.78     .05       0
#XS Ineff= 2 , 0
             520    2410
Permanent Ineff=
       F       F
Bank Sta=558.1,570.77
XS Rating Curve= 0 ,0
Exp/Cntr(USF)=0,0
Exp/Cntr=0.3,0.1

Type RM Length L Ch R = 1 ,730     ,390,390,390
XS GIS Cut Line= 6
2279040.20523856 446651.733072532279230.70547768446140.751210465
2279188.36123305445933.1380553312279149.60531585445819.851528152
2279079.85552307445706.983060346 2278606.8842721445663.010000454
#Sta/Elev= 30
       0  2413.3    68.6 2412.35   211.9 2406.81   267.4  2406.5   275.9 2405.42
   288.7 2406.66   361.3 2404.43   374.1 2406.27     404 2406.18   455.2  2403.5
   565.3  2404.5   589.8 2403.53   602.1 2404.69   642.9 2403.64   655.1 2404.63
   695.9 2403.25   728.6 2403.75   736.8 2402.76     749 2403.85   756.9 2403.34
   765.6 2402.73   776.2 2403.27   803.7 2405.79   996.2 2402.79  1033.4  2405.3
  1141.9 2407.44  1366.9 2408.19  1386.9 2409.74  1427.1 2419.55  1484.6 2422.35
#Mann= 3 ,-1,0
       0     .05       0   756.9    .045       0   776.2     .05       0
#XS Ineff= 2 , 0
             600 2409.31  810.37         2407.72
Permanent Ineff=
       F       F
Bank Sta=756.9,776.2
XS Rating Curve= 0 ,0
Exp/Cntr(USF)=0,0
Exp/Cntr=0.3,0.1

Type RM Length L Ch R = 1 ,340     ,,,
XS GIS Cut Line= 5
2279065.10698209446775.3861196012279351.30452444445960.021246353
2279333.41717804445697.6734992022278933.93310851445590.349420822
2278605.99842457445582.896359823
#Sta/Elev= 30
       0 2413.16   192.4 2409.99   277.1 2407.73   324.5 2404.96   366.9 2406.73
   390.1 2404.88   472.9 2405.11   502.6 2403.51   518.7 2405.05   676.4 2403.64
   744.2 2405.64   772.9 2402.84   842.6 2402.66   862.9 2405.49     891  2405.4
  1018.7 2402.96  1154.6 2401.88  1219.9    2403  1231.9 2401.18  1256.8 2400.68
  1291.22401.204  1308.1 2403.32  1360.3 2402.16  1388.7 2403.67  1451.7 2403.58
  1513.3 2405.41  1762.6 2406.41  1802.6 2408.43  1846.6 2415.91  1868.8  2418.2
#Mann= 6 ,-1,0
       0     .06       0      60     .05       0 1044.13     .08       0
 1187.09     .05       0  1231.9    .045       0  1291.2     .05       0
#XS Ineff= 2 , 0
         1218.66 2405.37 1311.14         2404.27
Permanent Ineff=
       F       F
Bank Sta=1231.9,1291.2
XS Rating Curve= 0 ,0
Exp/Cntr(USF)=0,0
Exp/Cntr=0.3,0.1
LCMann Table=0

Chan Stop Cuts=-1
Use User Specified Reach Order=0
Composite Channel Slope=5